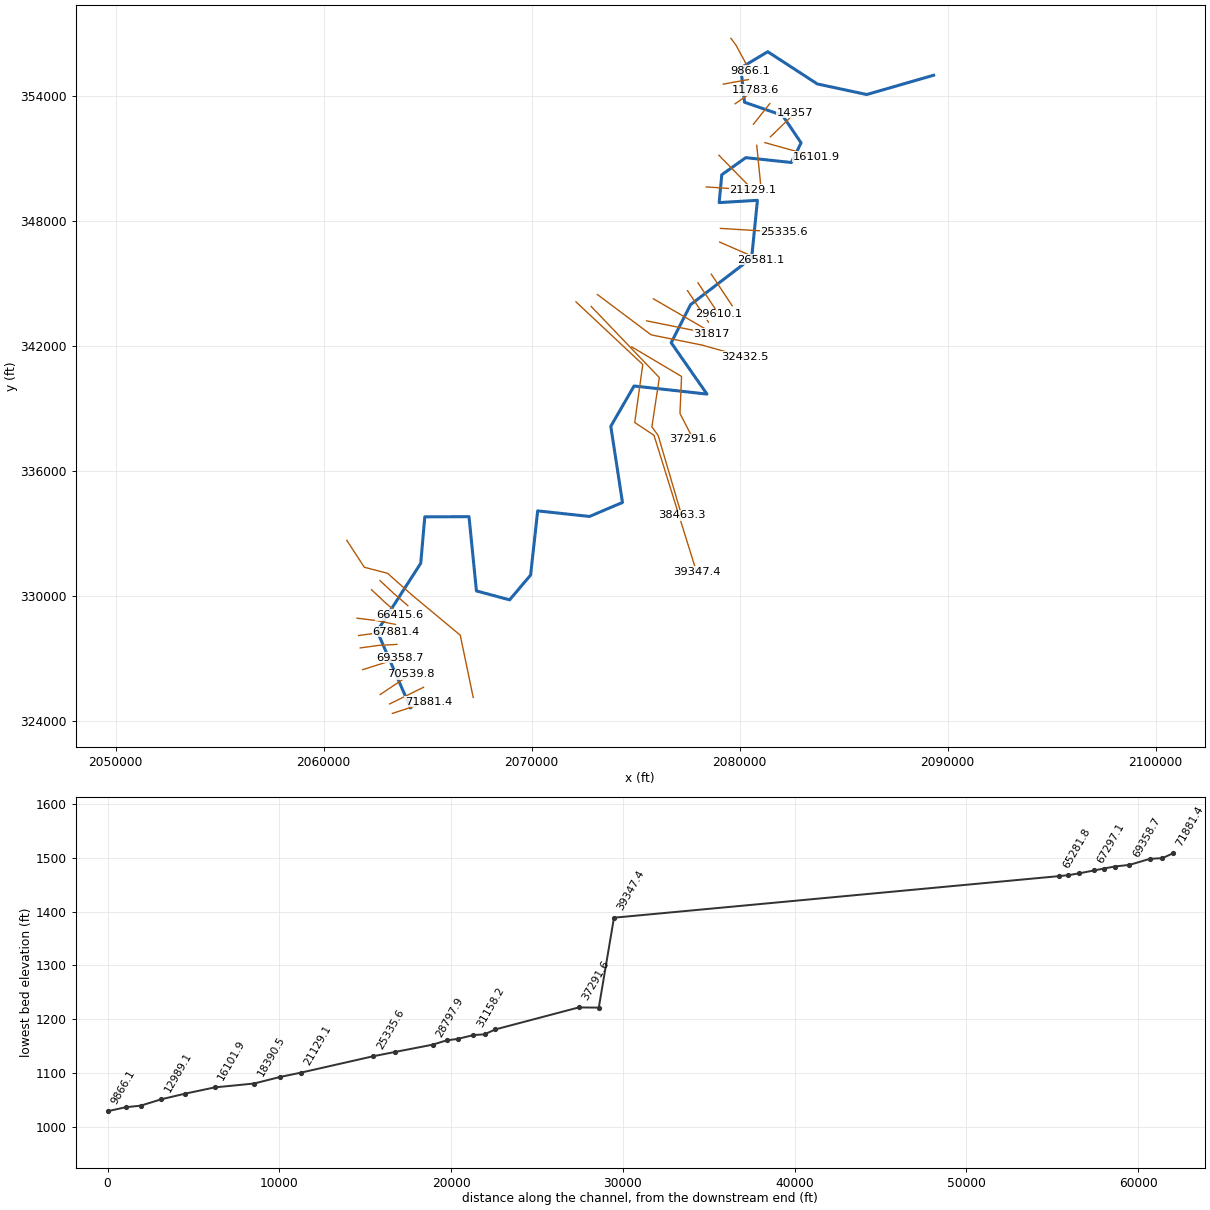
--- NBPOTRVR1.prj (project) ---

Proj Title=NBPOTRVR1
Current Plan=p01
Default Exp/Contr=0,0
English Units
Geom File=g01
Flow File=f01
Plan File=p01
BEGIN DESCRIPTION:
END DESCRIPTION:
DSS Export Rating Curves= 0
DSS Export Rating Curve Sorted= 0
DSS Export Volume Flow Curves= 0
DXF OffsetX= 0
DXF OffsetY= 0
DXF ScaleX= 0
DXF ScaleY= 0

--- NBPOTRVR1.p01 (plan) ---

Plan Title=Floodplain
Program Version=4.00
Geom File=g01
Flow File=f01
K Sum by GR=0
Std Step Tol=0.01
Critical Tol=0.01
Num of Std Step Trials=20
Max Error Tol=0.3
Flow Tol Ratio=0.001
Split Flow NTrial=30
Split Flow Tol=0.02
Split Flow Ratio=0.02
Log Output Level=0
Friction Slope Method=1
Unsteady Friction Slope Method=2
Unsteady Bridges Friction Slope Method=1
Global Log Level=0
CheckData=False
Run HTab=0
Run UNet=0
Run PostProcess=0
UNET Theta=0
UNET Theta Warmup=0
UNET ZTol=0
UNET ZSATol=0
UNET MxIter=0
UNET MaxInSteps=0
UNET DtIC=0
UNET DtMin=0
UNET MaxCRTS=0
UNET WFStab=0
UNET SFStab=0
UNET WFX=0
UNET SFX=0
UNET DSS MLevel=0
UNET DZMax Abort=0
UNET Convert EG Bridges=0
UNET Use Existing IB Tables=0
UNET Froude Limit=0
UNET Froude Power=0
Write IC File=0
Echo Input=False
Echo Output=False
Write Detailed=0

--- NBPOTRVR1.f01 (steady flow) ---

Flow Title=NFF Regression Equation
Program Version=4.00
Number of Profiles= 1
Profile Names=P100yr
River Rch & RM=NBPOTRVR1,Main            ,71881.4
   27806
River Rch & RM=NBPOTRVR1,Main            ,66415.6
   27905
River Rch & RM=NBPOTRVR1,Main            ,39347.4
   31003
Boundary for River Rch & Prof#=NBPOTRVR1,Main            , 1
Up Type= 0
Dn Type= 1
Dn Known WS=980
DSS Import GetInterval= 0
DSS Import GetPeak= 0
DSS Import FillOption= 0

--- NBPOTRVR1.g01 (geometry) ---

Geom Title=USGS 10m DEM
Program Version=4.00

River Reach=NBPOTRVR1       ,Main
Reach XY= 30
     2064175.684      324623.885     2062569.769      328298.931
     2064668.281      331560.203     2064862.577      333790.032
      2066988.84      333798.744     2067344.766      330232.532
      2068941.66      329803.435     2069949.012      330994.437
     2070289.568      334077.298     2072782.347      333809.442
     2074366.066      334481.351       2073804.1      338139.018
     2074923.243      340074.616     2078427.478       339686.92
     2076708.071      342153.419     2077639.646      343982.053
     2080575.973      346224.449      2080852.57      348993.083
     2079013.527       348883.95     2079140.552      350222.994
     2080292.862      351042.096      2082482.52      350810.105
     2082952.232      351752.298     2082059.099      353073.404
     2080232.335      353704.526     2080057.257      355356.035
     2081348.526      356130.859     2083732.831      354582.355
     2086106.496      354074.853     2089321.263      354999.331

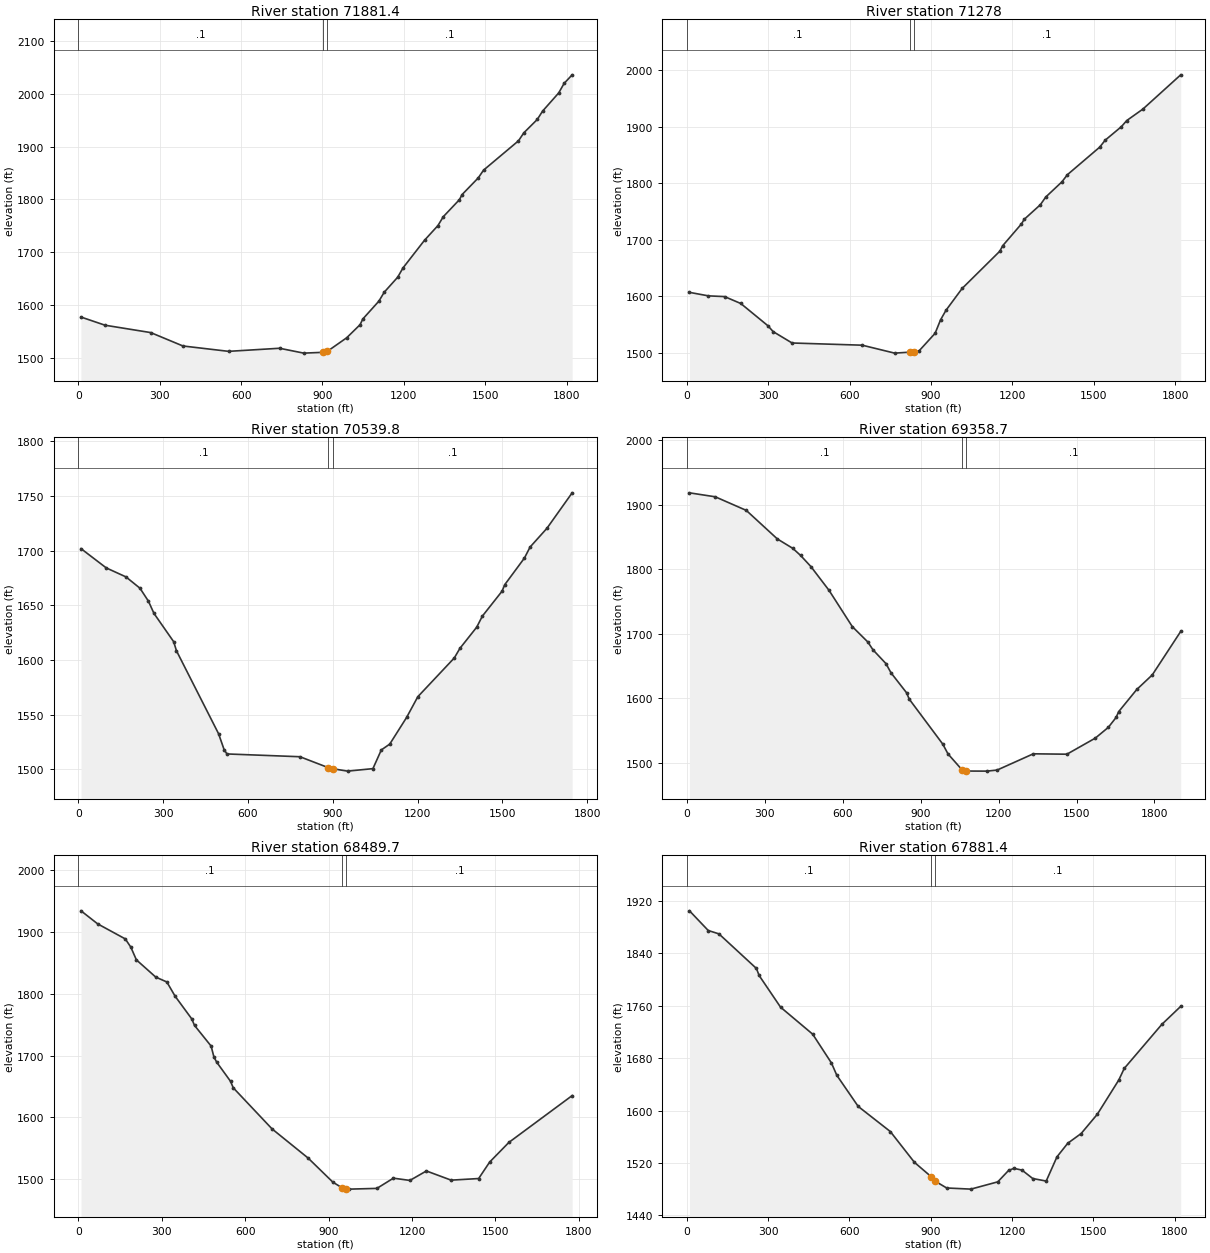
Type RM Length L Ch R = 1 ,71881.4 ,600.2,603.3,606.5
XS GIS Cut Line= 3
     2063307.487      324351.061     2064172.582      324633.391
     2065037.677      324915.721
#Sta/Elev= 30
     9.9  1576.8    98.9 1561.26   267.1 1547.29   385.8 1521.89   553.9 1511.71
   741.8 1517.56   830.9 1508.33   902.5 1509.85   917.5 1511.59   989.1 1537.39
  1038.6  1562.3  1048.5    1573  1107.8 1606.87  1127.6  1623.9  1177.1  1652.3
  1196.8 1669.99    1276 1722.41  1325.4  1750.2  1345.2  1767.1  1404.6 1799.37
  1414.5 1809.08  1473.8 1840.54  1493.6 1855.38  1622.2 1910.97    1642 1926.18
  1691.4 1951.44  1711.2 1967.38  1770.5 2001.83  1790.3 2019.84    1820 2036.13
#Mann= 3 , 0 , 0
       0      .1       0   902.5    .045       0   917.5      .1       0
Bank Sta=902.5,917.5
XS Rating Curve= 0 ,0
Exp/Cntr=0.3,0.1

Type RM Length L Ch R = 1 ,71278   ,735.2,738.2,741.3
XS GIS Cut Line= 2
     2063169.867      324802.131     2064802.993      325605.437
#Sta/Elev= 30
     9.9 1607.07    79.6 1600.86   139.2 1599.57   198.9 1587.36   298.4 1548.18
   318.3 1537.57   387.9 1517.47   646.4 1513.57   765.8 1499.54   820.7 1501.21
   835.7 1500.94   855.3 1503.22     915 1534.64   934.9 1558.29   954.8 1575.17
  1014.4  1613.9  1153.7 1680.03  1163.6 1689.37  1233.2 1728.23  1243.2 1736.22
  1302.8 1762.12  1322.7 1775.75  1382.4 1802.68  1402.3  1815.2  1521.6 1864.06
  1541.5 1876.25  1601.2 1900.18  1621.1 1911.05  1680.8 1931.42    1820 1991.97
#Mann= 3 , 0 , 0
       0      .1       0   820.7    .045       0   835.7      .1       0
Bank Sta=820.7,835.7
XS Rating Curve= 0 ,0
Exp/Cntr=0.3,0.1

Type RM Length L Ch R = 1 ,70539.8 ,1187.5,1181.1,1174.7
XS GIS Cut Line= 2
     2062719.852      325256.273     2064172.408      326226.058
#Sta/Elev= 30
     9.9 1701.84    99.2  1684.2   168.7    1676   218.3 1665.62   248.1 1653.81
   267.9 1642.51   337.4 1616.68   347.3 1608.36   496.2 1532.41     516 1517.69
   525.9 1513.89     784 1511.34   884.9 1501.28   899.9 1500.34   952.7 1498.16
    1042 1500.44  1071.7 1517.56  1101.5  1522.9  1161.1  1547.3  1200.7 1566.26
  1329.8 1601.79  1349.6 1610.55  1409.1 1629.98    1429 1640.08  1498.5 1662.86
  1508.4 1668.94  1577.8 1693.27  1597.7 1703.31  1657.2 1720.44  1746.5 1752.96
#Mann= 3 , 0 , 0
       0      .1       0   884.9    .045       0   899.9      .1       0
Bank Sta=884.9,899.9
XS Rating Curve= 0 ,0
Exp/Cntr=0.3,0.1

Type RM Length L Ch R = 1 ,69358.7 ,874.8,869,863.3
XS GIS Cut Line= 2
     2061874.851      326449.094      2063686.75      327024.583
#Sta/Elev= 30
      10 1918.72   109.5 1912.56   228.9 1891.48   348.4 1847.21   408.1 1832.53
   437.9 1821.61   477.8 1804.25   547.4 1767.45     637 1711.17   696.7 1687.35
   716.6 1675.16   766.4 1653.84   786.3 1639.32     846 1608.48     856 1598.74
   985.4  1528.8  1005.3 1513.69  1060.3 1488.56  1075.3  1487.1  1154.6 1486.96
  1194.4  1488.6  1333.8 1513.83  1463.1 1513.21  1572.6 1538.23  1622.4 1554.84
  1652.3 1570.19  1662.2 1579.18  1731.9  1613.6  1791.6 1636.22  1901.1 1703.68
#Mann= 3 , 0 , 0
       0      .1       0  1060.3    .045       0  1075.3      .1       0
Bank Sta=1060.3,1075.3
XS Rating Curve= 0 ,0
Exp/Cntr=0.3,0.1

Type RM Length L Ch R = 1 ,68489.7 ,606.5,608.3,608.3
XS GIS Cut Line= 3
     2061760.721      327495.583     2062638.729      327614.313
     2063527.276       327664.51
#Sta/Elev= 30
      10 1934.39    69.7 1913.33   169.2 1888.92   189.1 1875.59   209.1 1855.01
   278.7 1827.14   318.6 1819.23   348.4 1796.15   408.2 1759.48   418.1 1748.92
   477.8 1715.49   487.8 1697.98   497.8 1689.48   547.5 1658.53   557.5 1647.91
   696.9 1581.44   826.3 1534.36   915.7 1495.21   949.3 1485.92   964.3 1484.05
     975 1483.96  1073.9 1485.15  1133.2 1501.69  1192.5 1498.04  1251.9 1513.35
  1340.9 1498.49  1439.8  1501.1  1479.3 1527.72  1548.5 1559.57    1776 1635.33
#Mann= 3 , 0 , 0
       0      .1       0   949.3    .045       0   964.3      .1       0
Bank Sta=949.3,964.3
XS Rating Curve= 0 ,0
Exp/Cntr=0.3,0.1

Type RM Length L Ch R = 1 ,67881.4 ,591.8,584.2,578.5
XS GIS Cut Line= 3
     2061680.316      328090.171     2062581.519      328212.038
     2063493.433      328263.555
#Sta/Elev= 30
     9.9 1904.93    79.1  1874.9   118.6 1869.76     257 1816.94   266.9 1806.24
     346  1757.9   464.6 1716.67   533.8 1672.73   553.6 1653.94   632.6 1606.41
   751.2 1568.06   840.2 1521.03   901.9  1499.2   916.9 1492.28     959 1481.98
  1048.4 1480.22  1147.7 1491.34  1187.4 1508.68  1207.2 1511.93    1237 1509.25
  1276.7  1496.4  1326.4 1492.54  1366.1 1529.48  1405.8 1550.18  1455.4 1565.09
    1515 1594.46  1594.4 1646.84  1614.3 1664.38  1753.3 1731.72  1822.8 1759.12
#Mann= 3 , 0 , 0
       0      .1       0   901.9    .045       0   916.9      .1       0
Bank Sta=901.9,916.9
XS Rating Curve= 0 ,0
Exp/Cntr=0.3,0.1

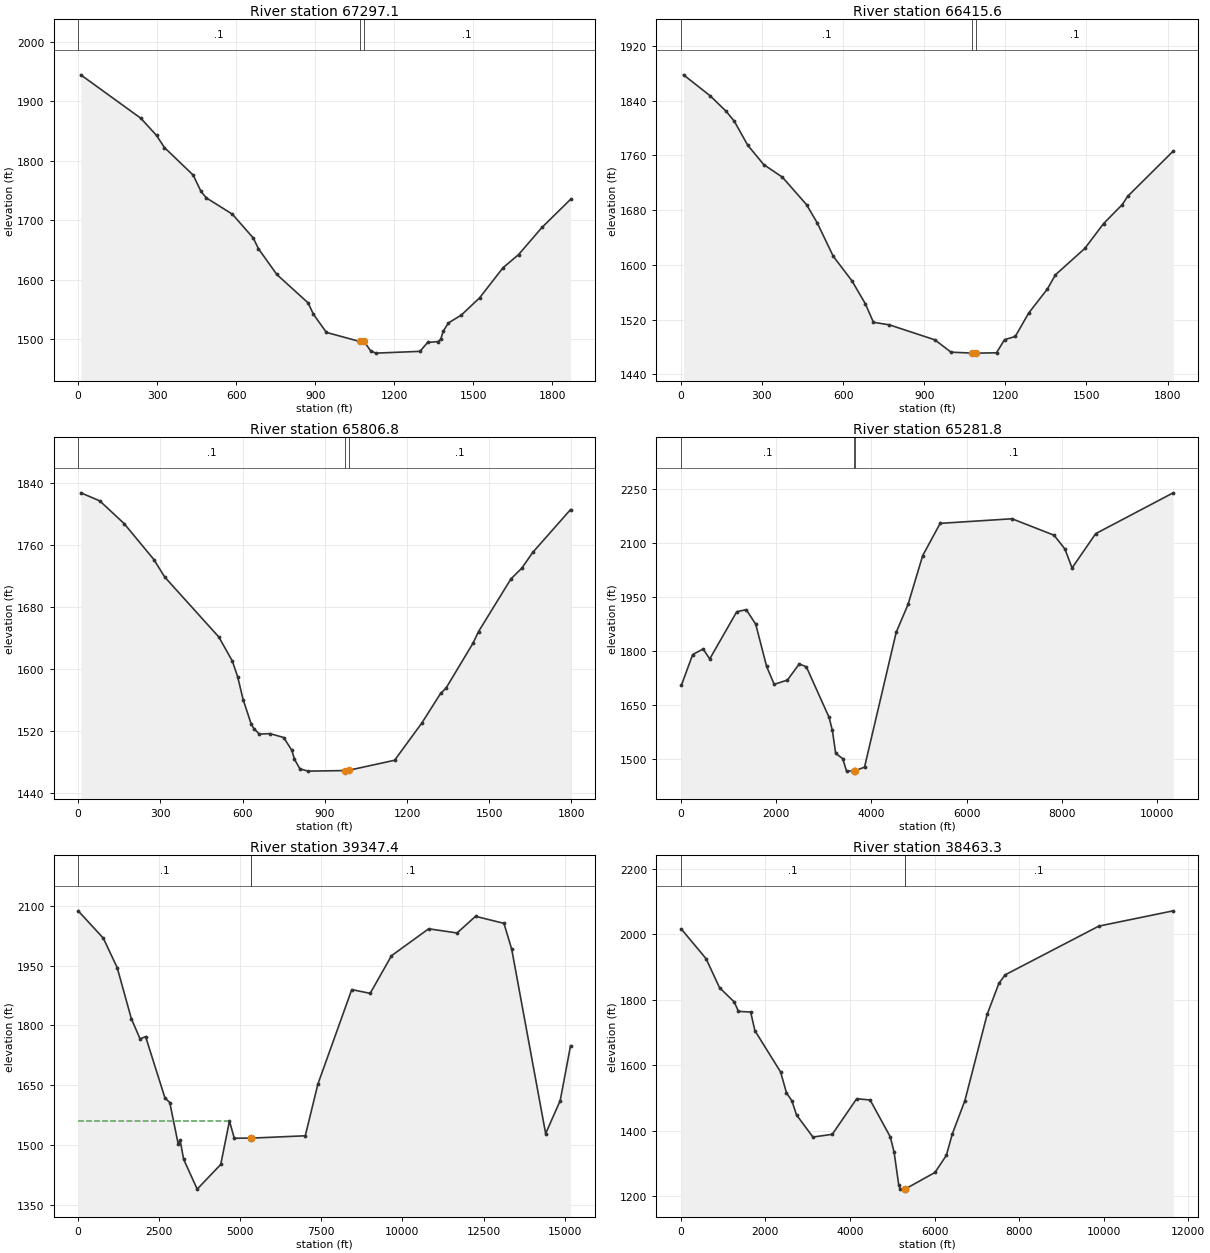
Type RM Length L Ch R = 1 ,67297.1 ,893.2,881.5,869.8
XS GIS Cut Line= 3
     2061607.601      328922.497     2062533.599      328809.967
     2063451.902      328624.861
#Sta/Elev= 30
     9.9 1944.56   238.2 1871.46   297.7 1842.59   327.5 1822.33   436.6 1776.07
   466.4 1748.51   486.3 1737.75   585.5 1710.29   664.9 1670.21   684.7 1652.15
   754.2 1608.93   873.3 1561.03   893.1 1542.16   942.7 1511.44    1069 1496.22
    1084 1497.37  1110.3 1480.53    1130 1476.62  1297.7  1479.6  1327.2 1494.64
  1366.7 1496.07  1376.5 1499.73  1386.4 1513.79  1406.1 1527.42  1455.4  1540.8
  1524.5 1569.71  1613.2 1620.17  1672.4 1642.37  1761.1 1687.94  1869.6 1735.19
#Mann= 3 , 0 , 0
       0      .1       0    1069    .045       0    1084      .1       0
Bank Sta=1069,1084
XS Rating Curve= 0 ,0
Exp/Cntr=0.3,0.1

Type RM Length L Ch R = 1 ,66415.6 ,608.7,608.8,608.9
XS GIS Cut Line= 3
     2062301.028      330289.855     2062965.482      329668.309
     2063654.907      329073.006
#Sta/Elev= 30
     9.9 1877.84   108.8 1847.06   168.1 1824.32   197.8 1809.98   247.2 1775.08
   306.6 1746.66   375.8 1728.19   464.8 1688.15   504.4 1661.45   563.7 1612.68
   632.9 1576.72   682.4  1543.2   712.1 1516.28   771.4 1512.45   939.5 1490.57
     999 1472.55    1078  1471.2  1088.1 1471.16    1093 1471.16  1167.3 1471.64
    1197 1490.86  1236.6 1495.46  1286.1 1529.61  1355.4 1564.87  1385.1 1585.57
    1494 1624.22  1563.3 1660.55  1632.6 1688.32  1652.4 1700.36  1820.7 1766.38
#Mann= 3 , 0 , 0
       0      .1       0    1078    .045       0    1093      .1       0
Bank Sta=1078,1093
XS Rating Curve= 0 ,0
Exp/Cntr=0.3,0.1

Type RM Length L Ch R = 1 ,65806.8 ,525.4,525.1,524.8
XS GIS Cut Line= 3
     2062710.908      330728.031     2063366.646      330114.638
     2064047.038      329527.136
#Sta/Elev= 30
     9.9 1826.79    78.9 1816.41   167.7 1787.14   276.3 1740.76   315.7 1718.26
   513.1 1640.94   562.4 1610.06   582.2 1589.39   601.9 1560.23   631.5 1528.57
   641.4 1522.68   661.1 1515.67   700.6 1516.23   749.9 1511.23   779.5 1494.89
   789.4 1483.25   809.1 1470.87   838.7 1467.87     975  1468.6     990 1469.18
  1154.7 1481.87  1253.5 1529.62  1322.7  1568.1  1342.4  1574.9  1441.2 1633.05
    1461 1647.83  1579.5 1715.89    1619 1729.66  1658.6 1749.84  1796.8 1805.19
#Mann= 3 , 0 , 0
       0      .1       0     975    .045       0     990      .1       0
Bank Sta=975,990
XS Rating Curve= 0 ,0
Exp/Cntr=0.3,0.1

Type RM Length L Ch R = 1 ,65281.8 ,25984.6,25934.4,25884.2
XS GIS Cut Line= 6
      2061114.26      332661.065     2061957.132      331368.377
     2063072.931      331078.483     2064276.734      330010.527
     2066567.643      328107.621     2067191.313      325113.725
#Sta/Elev= 30
      10 1704.06   248.9 1790.03   467.9 1805.49   607.3 1777.94  1174.8 1909.11
  1373.9 1914.72    1573 1874.37  1801.6 1757.06  1960.6 1707.17  2238.9  1719.2
  2487.3 1763.96  2636.4    1756  3113.3 1615.59  3182.8 1579.51  3252.3 1515.72
  3401.3 1500.59  3480.8 1466.16  3643.1 1466.99  3658.1 1467.03  3858.3 1477.28
  4523.7 1852.07  4771.9 1929.16  5079.6 2064.87  5446.9 2154.49  6955.8 2167.28
  7839.5 2121.51  8067.8 2083.14  8216.8  2030.6  8713.2 2125.92 10341.6 2239.33
#Mann= 3 , 0 , 0
       0      .1       0  3643.1    .045       0  3658.1      .1       0
Bank Sta=3643.1,3658.1
XS Rating Curve= 0 ,0
Exp/Cntr=0.3,0.1

Type RM Length L Ch R = 1 ,39347.4 ,884.4,884.1,883.8
XS GIS Cut Line= 5
     2072127.699      344118.107     2075342.181      341108.712
     2074955.411      338321.985     2075882.116        337704.8
     2077920.504      331164.063
#Sta/Elev= 30
     9.9 2087.66   785.2 2018.98  1212.7 1944.98    1650 1816.49  1918.4 1765.91
  2087.4 1771.84  2683.7 1617.87  2832.8 1606.11  3091.3 1502.57  3150.9 1511.58
  3260.3 1463.63  3677.7 1388.71  4403.3 1450.69  4671.8 1559.74  4820.9  1516.5
  5335.8 1516.97  5350.8 1516.83    7008 1522.68  7395.7 1652.29  8439.7 1889.84
  9007.3 1880.39  9664.5 1974.93 10809.7 2042.54   11686 2032.05 12253.6 2073.89
 13129.9 2056.17 13368.9 1991.19 14414.4  1528.2 14862.5 1611.03 15181.2 1748.87
#Mann= 3 , 0 , 0
     9.9      .1       0  5335.8    .045       0  5350.8      .1       0
#XS Ineff= 2 , 0
         4675.48 1560.06
Permanent Ineff=
       F       F
Bank Sta=5335.8,5350.8
XS Rating Curve= 0 ,0
Exp/Cntr=0.3,0.1

Type RM Length L Ch R = 1 ,38463.3 ,1169.1,1171.7,1174.3
XS GIS Cut Line= 5
     2072860.526      343896.917     2076137.877       340478.42
     2075780.128      338115.616       2076080.8      337698.849
     2077211.557      333857.434
#Sta/Elev= 30
     9.9 2016.36   596.9 1925.65   915.3 1837.02  1263.5 1793.28    1363  1764.6
  1651.5 1762.58    1751 1705.83  2357.9 1579.77  2497.2 1516.28  2626.5 1491.13
    2736 1448.13    3124 1380.57  3581.6 1389.03  4158.7 1497.71  4477.1 1493.78
  4954.8 1380.81  5044.4 1333.56  5153.9 1233.64  5193.8 1221.49  5292.9 1221.51
  5307.9 1221.95  6010.3 1272.48  6279.1  1324.6  6418.5 1389.62  6717.2 1491.75
  7244.1 1755.51  7520.8 1849.92  7669.2  1876.2    9885  2025.1 11643.8 2071.78
#Mann= 3 , 0 , 0
       0      .1       0  5292.9    .045       0  5307.9      .1       0
Bank Sta=5292.9,5307.9
XS Rating Curve= 0 ,0
Exp/Cntr=0.3,0.1

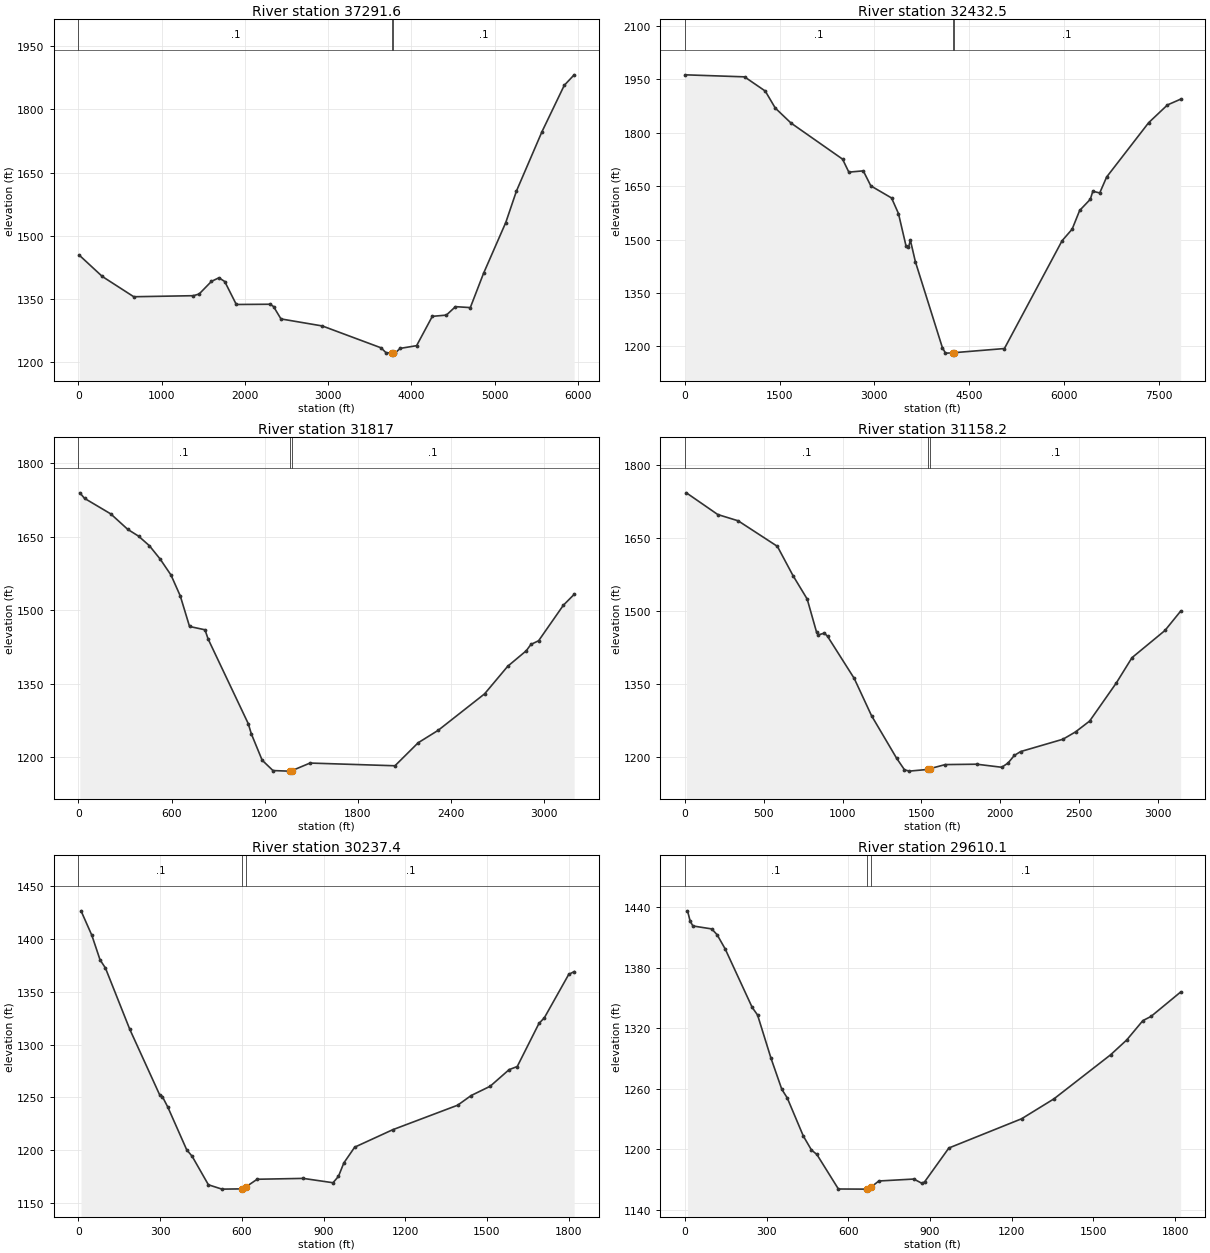
Type RM Length L Ch R = 1 ,37291.6 ,4827.1,4859.1,4891
XS GIS Cut Line= 4
     2074804.956      341958.042      2077206.42      340533.206
     2077129.267      338756.398     2077764.667      337524.396
#Sta/Elev= 30
     9.9  1454.3   288.2  1403.5   665.8 1355.48  1381.3 1357.95  1450.8 1361.88
  1599.9 1391.97  1689.3 1400.42  1758.9 1391.57    1898 1337.13  2305.4  1337.7
  2345.2  1332.2  2434.6 1302.87  2931.4 1286.21  3636.9 1234.36  3696.5 1222.83
    3771 1222.07    3786 1221.98  3805.8 1221.79  3865.4 1232.99  4064.1 1239.47
  4252.9 1308.98  4421.8 1311.97  4531.1 1331.96  4709.4 1329.75  4867.9 1410.75
  5135.2 1531.38  5263.9 1606.18  5570.9 1747.02  5838.2 1856.74    5957 1881.62
#Mann= 3 , 0 , 0
       0      .1       0    3771    .045       0    3786      .1       0
Bank Sta=3771,3786
XS Rating Curve= 0 ,0
Exp/Cntr=0.3,0.1

Type RM Length L Ch R = 1 ,32432.5 ,615.5,615.5,615.4
XS GIS Cut Line= 4
     2073158.122      344470.539     2075743.473      342531.627
     2078184.654      342042.568     2080228.628      341468.025
#Sta/Elev= 30
     9.9 1962.58   944.6 1956.91  1272.8 1917.03  1431.9 1869.11  1680.4 1827.12
  2495.8 1725.79  2595.2 1689.24  2823.9 1692.83  2943.3 1650.65  3271.3 1616.66
  3380.4 1572.94  3499.4 1482.41  3539.1 1477.89  3568.9  1497.9  3648.2 1437.52
  4074.7 1196.53  4124.3 1180.82  4240.2 1181.42  4255.2    1182  5056.7 1193.71
  5969.4 1496.64  6128.1 1529.02  6247.2 1581.64  6415.8 1613.06  6455.5 1635.54
  6564.6 1630.78  6673.8 1675.48  7338.5  1828.1  7636.2 1878.03  7844.5 1894.15
#Mann= 3 , 0 , 0
       0      .1       0  4240.2    .045       0  4255.2      .1       0
Bank Sta=4240.2,4255.2
XS Rating Curve= 0 ,0
Exp/Cntr=0.3,0.1

Type RM Length L Ch R = 1 ,31817   ,666.1,658.8,651.5
XS GIS Cut Line= 2
     2075523.852      343205.552     2078652.862       342573.18
#Sta/Elev= 30
     9.9 1739.19    39.8 1727.96   208.8 1696.23   318.2  1664.7   387.8 1650.88
   457.5 1631.38   527.1 1604.04   596.7 1571.52   656.4 1528.96     716 1466.74
   815.5 1459.95   835.4 1441.33  1093.9 1268.69  1113.8  1247.9  1183.4 1194.18
    1253 1173.02  1352.5 1171.84  1360.6 1171.88  1375.6 1172.89  1491.7  1188.3
  2038.7 1182.77  2187.8 1229.62  2317.1  1255.1  2615.5 1329.34  2764.6 1385.63
    2884 1417.25  2913.8 1430.07  2963.5 1437.67  3122.7 1509.99  3192.3 1532.22
#Mann= 3 , 0 , 0
       0      .1       0  1360.6    .045       0  1375.6      .1       0
Bank Sta=1360.6,1375.6
XS Rating Curve= 0 ,0
Exp/Cntr=0.3,0.1

Type RM Length L Ch R = 1 ,31158.2 ,931.4,920.8,910.3
XS GIS Cut Line= 2
     2075850.469      344263.465     2078570.659      342689.076
#Sta/Elev= 30
     9.9 1743.55   208.9 1698.85   338.2 1685.91   586.8 1633.33   686.3  1572.8
   775.8 1524.73   835.5 1456.24   845.4 1450.88   885.2 1454.59   905.1 1447.83
  1074.2 1361.15  1183.6 1284.55  1342.7 1196.89  1392.4 1173.16  1422.3 1170.33
  1542.3 1173.88  1557.3 1175.74    1651  1183.8    1850 1184.59  2009.1 1178.27
  2048.9 1187.01  2088.7 1202.64  2128.5 1210.58    2397 1236.04  2476.6 1251.09
  2566.1 1273.45  2735.2 1351.92  2834.6 1404.01  3043.5 1459.99  3142.9  1499.8
#Mann= 3 , 0 , 0
       0      .1       0  1542.3    .045       0  1557.3      .1       0
Bank Sta=1542.3,1557.3
XS Rating Curve= 0 ,0
Exp/Cntr=0.3,0.1

Type RM Length L Ch R = 1 ,30237.4 ,627.3,627.3,627.3
XS GIS Cut Line= 2
     2077493.556      344655.273     2078499.476      343138.524
#Sta/Elev= 30
     9.9 1426.67    49.7 1403.42    79.6 1380.33    99.5 1372.51     189  1314.4
   298.4 1252.52   308.3 1250.86   328.2 1240.99   397.8 1200.41   417.7  1194.3
   477.4 1167.31   527.1 1163.18   601.9 1163.42   616.9  1165.6   656.4 1172.53
   825.5 1173.34   934.9 1169.23   954.8 1175.26   974.6 1187.98  1014.4 1202.91
  1153.7 1219.39  1392.3 1242.63  1442.1 1251.82  1511.7 1260.58  1581.3 1276.32
  1611.1 1279.26  1690.7 1320.02  1710.6  1325.4  1800.1  1366.5    1820 1369.11
#Mann= 3 , 0 , 0
       0      .1       0   601.9    .045       0   616.9      .1       0
Bank Sta=601.9,616.9
XS Rating Curve= 0 ,0
Exp/Cntr=0.3,0.1

Type RM Length L Ch R = 1 ,29610.1 ,812,812.2,812.3
XS GIS Cut Line= 3
     2077993.583      345033.523     2078496.543      344275.149
     2078999.503      343516.775
#Sta/Elev= 30
     9.9 1436.11    19.8 1425.91    29.7 1421.13    98.9  1418.2   118.7 1412.42
   148.4 1398.31   247.3 1340.54   267.1 1332.98   316.5 1290.12   356.1 1259.43
   375.9 1250.99   435.2 1213.11   464.9 1199.37   484.7 1194.98   563.8 1160.76
   662.7 1160.63   668.9 1160.85   683.9 1162.71   712.2 1168.68   840.8 1170.61
   870.4 1166.37   880.3 1167.84   969.3 1201.34  1236.4 1230.29  1355.1    1250
  1562.8 1293.56  1622.2  1308.3  1681.5 1327.46  1711.2 1331.54    1820 1355.72
#Mann= 3 , 0 , 0
       0      .1       0   668.9    .045       0   683.9      .1       0
Bank Sta=668.9,683.9
XS Rating Curve= 0 ,0
Exp/Cntr=0.3,0.1

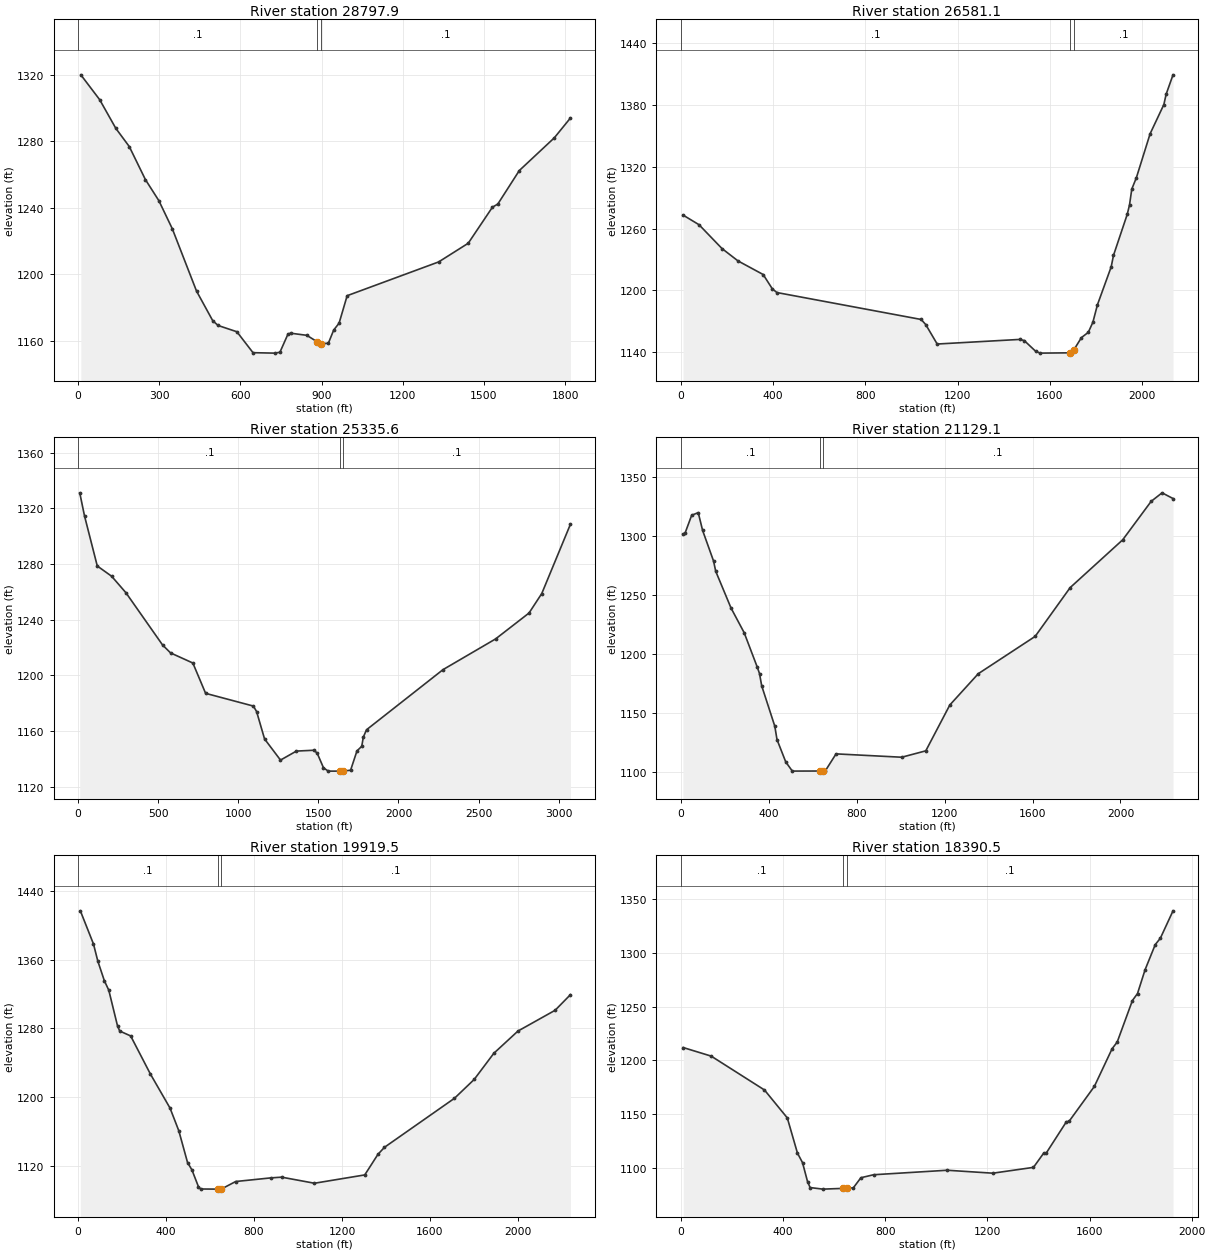
Type RM Length L Ch R = 1 ,28797.9 ,2203.8,2216.8,2229.9
XS GIS Cut Line= 2
     2078634.525      345445.668     2079640.444       343928.92
#Sta/Elev= 30
     9.9    1320    79.6 1305.04   139.2 1287.81     189 1276.85   248.6 1256.99
   298.4 1244.29   348.1 1227.38   437.6 1189.92   497.3 1172.16   517.2 1169.22
   586.8 1165.44   646.4 1152.85     726 1152.58   745.9 1153.09   775.7 1164.03
   785.7 1164.57   845.4 1163.29   882.4 1159.54   897.4 1158.35   924.9 1158.48
   944.8 1166.48   964.7 1170.61   994.5 1187.13  1332.7 1207.44  1442.1 1218.68
  1531.6 1240.37  1551.5 1242.27    1631 1262.43  1760.3 1282.09    1820 1294.04
#Mann= 3 , 0 , 0
       0      .1       0   882.4    .045       0   897.4      .1       0
Bank Sta=882.4,897.4
XS Rating Curve= 0 ,0
Exp/Cntr=0.3,0.1

Type RM Length L Ch R = 1 ,26581.1 ,1237.8,1245.4,1253
XS GIS Cut Line= 2
     2079042.088       346984.71     2081000.501      346136.064
#Sta/Elev= 30
     9.9  1273.1    79.4 1263.69   178.7 1240.57   248.2 1228.52   357.4 1215.28
   397.1 1201.36   416.9 1197.76  1042.4 1171.57  1062.2 1166.63  1111.9 1147.69
  1469.2 1152.16  1489.1  1151.1  1538.7 1140.68  1558.6 1138.84    1688 1139.13
    1703 1141.48  1737.3 1153.94  1767.1 1159.07  1786.9 1168.83  1806.8 1185.92
  1866.3 1222.71  1876.3  1233.9  1935.8 1273.72  1945.8 1282.96  1955.7 1298.42
  1975.5 1309.38  2035.1 1352.18  2094.7 1380.56  2104.6 1390.61  2134.4 1409.46
#Mann= 3 , 0 , 0
       0      .1       0    1688    .045       0    1703      .1       0
Bank Sta=1688,1703
XS Rating Curve= 0 ,0
Exp/Cntr=0.3,0.1

Type RM Length L Ch R = 1 ,25335.6 ,4206.2,4206.6,4206
XS GIS Cut Line= 2
     2079076.432      347644.008     2082144.613      347457.492
#Sta/Elev= 30
     9.9  1331.1    39.8 1314.45   119.4 1278.51   208.9 1271.15   298.4 1259.27
   527.2 1221.71     577 1216.03   716.2 1208.76   795.8 1186.97  1094.2 1177.81
  1114.1 1173.89  1163.9 1154.19  1263.4 1138.98  1362.8 1145.46  1472.3 1146.06
  1492.2 1144.03  1531.9 1133.43  1561.8 1131.05  1637.9 1131.06  1652.9 1131.06
  1701.1  1131.7  1740.9 1145.59  1770.7  1148.9  1780.6  1155.5  1800.5 1160.78
    2278 1203.99  2606.3 1226.07  2815.2  1244.7  2894.8 1258.72  3073.8 1308.54
#Mann= 3 , 0 , 0
       0      .1       0  1637.9    .045       0  1652.9      .1       0
Bank Sta=1637.9,1652.9
XS Rating Curve= 0 ,0
Exp/Cntr=0.3,0.1

Type RM Length L Ch R = 1 ,21129.1 ,1226.1,1209.6,1193
XS GIS Cut Line= 2
     2078396.262      349635.709     2080630.551      349489.529
#Sta/Elev= 30
      10 1301.78    19.9 1302.79    49.8 1317.83    79.6 1320.07    99.5 1304.96
   149.3 1278.96   159.2 1270.26   228.9 1239.01   288.6 1218.09   348.3 1188.77
   358.3 1183.42   368.2 1173.03   427.9 1138.68   437.9 1127.33   477.7 1108.36
   507.5  1100.6   632.7 1100.65   647.7 1100.63   656.8 1100.56   706.5 1115.21
  1005.1 1112.36  1114.6 1117.79    1224 1156.74  1353.4 1183.29  1612.1 1214.98
  1771.3  1256.4  2010.2 1296.97  2139.6 1329.62  2189.3 1336.88  2239.1 1332.04
#Mann= 3 , 0 , 0
       0      .1       0   632.7    .045       0   647.7      .1       0
Bank Sta=632.7,647.7
XS Rating Curve= 0 ,0
Exp/Cntr=0.3,0.1

Type RM Length L Ch R = 1 ,19919.5 ,1544.3,1529,1513.7
XS GIS Cut Line= 2
     2079002.287      351156.919     2080569.158      349557.441
#Sta/Elev= 30
      10 1416.97    69.7  1378.3    89.6  1358.2   119.4 1335.32   139.3 1324.46
   179.1 1282.75   189.1 1276.84   238.8 1271.13   328.4 1226.82     418 1186.96
   457.8 1160.59   497.6  1123.5   517.5 1114.99   547.3 1095.27   557.3 1092.72
   636.5 1092.56   651.5 1092.69   716.5 1101.43   875.7 1105.65   925.5 1106.51
  1074.8 1099.42  1303.6 1109.13  1363.3 1133.03  1393.2 1141.31  1711.6 1198.44
  1801.2 1220.39  1890.8 1250.95  2000.2 1276.79  2169.4 1301.05  2239.1 1319.23
#Mann= 3 , 0 , 0
       0      .1       0   636.5    .045       0   651.5      .1       0
Bank Sta=636.5,651.5
XS Rating Curve= 0 ,0
Exp/Cntr=0.3,0.1

Type RM Length L Ch R = 1 ,18390.5 ,2260.9,2288.7,2316.4
XS GIS Cut Line= 2
     2080820.285      351635.131     2081011.517      349717.827
#Sta/Elev= 30
     9.9 1212.04   119.2 1204.08   327.8 1172.54   417.1 1146.56   456.9 1113.76
   476.7 1104.92   496.6 1087.03   506.5 1081.72   556.2 1080.26   636.1 1080.95
   651.1 1081.03   675.4 1081.43   705.2 1090.87   754.8 1093.65  1042.9 1097.84
  1221.6  1095.1  1380.6 1100.52  1420.3 1113.67  1430.2 1113.69  1509.7 1143.07
  1519.6 1143.25  1618.9 1175.85  1688.4 1210.97  1708.3 1217.16  1767.9 1255.84
  1787.8 1262.34  1817.6 1284.57  1857.3 1307.92  1877.2  1313.8  1926.8 1339.33
#Mann= 3 , 0 , 0
       0      .1       0   636.1    .045       0   651.1      .1       0
Bank Sta=636.1,651.1
XS Rating Curve= 0 ,0
Exp/Cntr=0.3,0.1

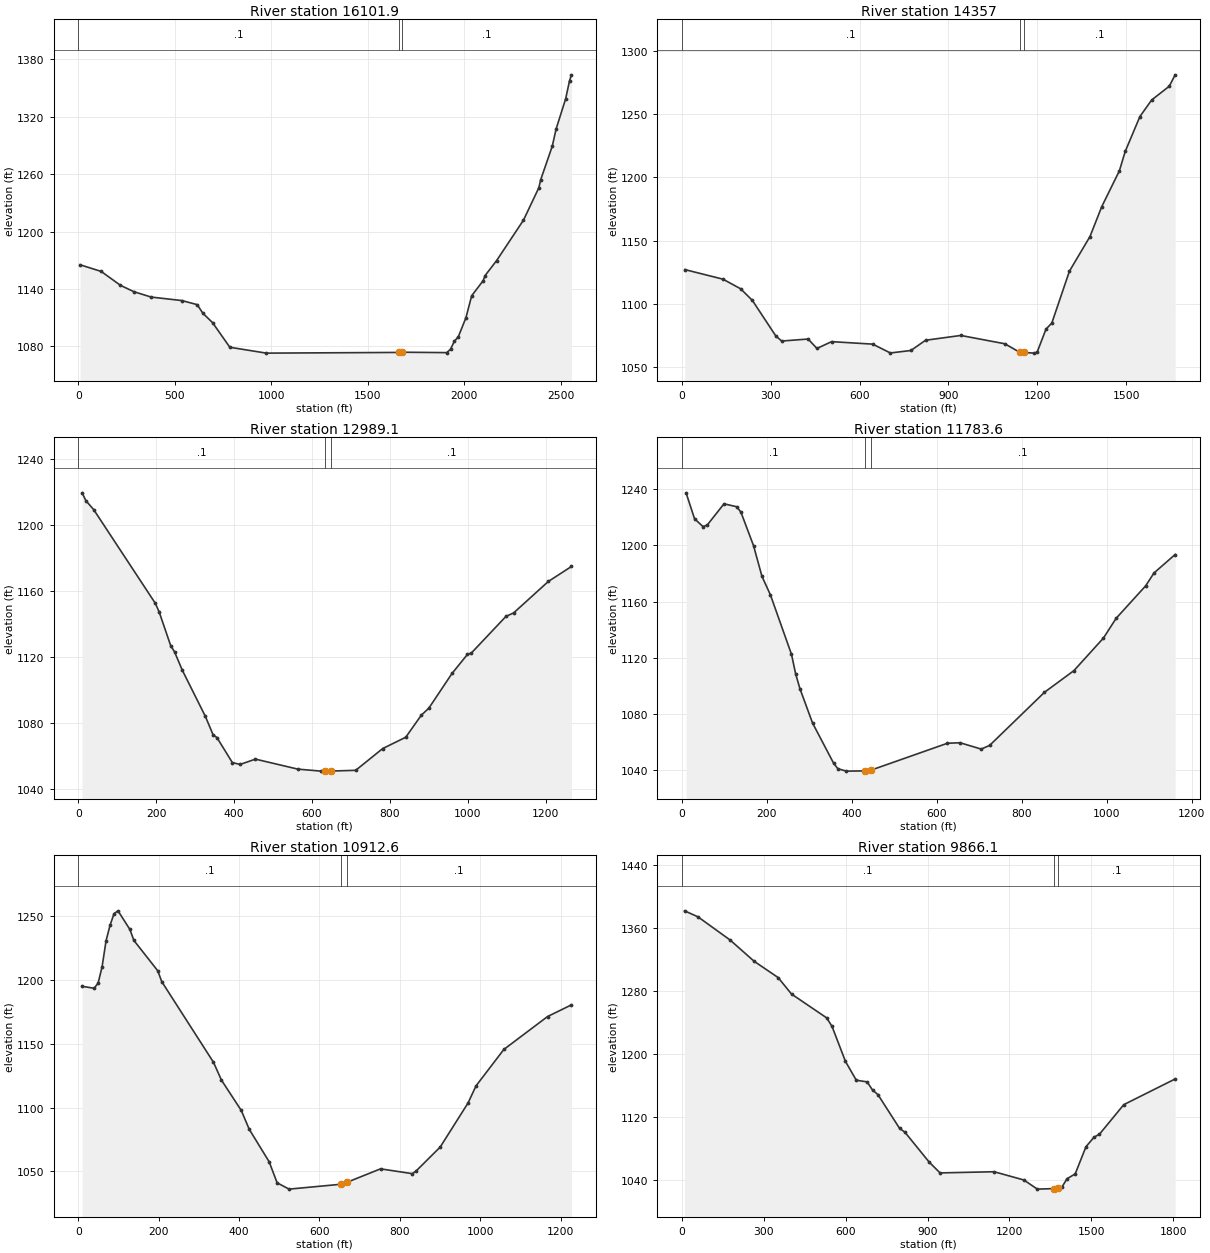
Type RM Length L Ch R = 1 ,16101.9 ,1721,1744.9,1768.7
XS GIS Cut Line= 2
     2081212.204      351763.868     2083674.989      351077.693
#Sta/Elev= 30
     9.9 1165.34   119.4 1158.38   218.9 1143.88   288.5 1137.23     378 1131.62
   537.2 1127.97   616.8  1123.7   646.6  1114.6   696.3 1104.93   785.9 1079.17
   974.9 1073.05  1662.5 1073.78  1677.5    1074    1910 1073.57  1929.9 1077.18
  1949.8 1085.58  1969.7 1089.95  2009.5 1110.02  2039.3 1132.98    2099  1148.8
  2108.9 1154.09  2168.6 1169.75  2307.9 1212.02  2387.5 1245.88  2397.4 1254.43
  2457.1  1289.3    2477 1307.22  2526.7 1338.97  2546.6 1357.72  2556.6  1363.8
#Mann= 3 , 0 , 0
       0      .1       0  1662.5    .045       0  1677.5      .1       0
Bank Sta=1662.5,1677.5
XS Rating Curve= 0 ,0
Exp/Cntr=0.3,0.1

Type RM Length L Ch R = 1 ,14357   ,1364.9,1367.9,1370.8
XS GIS Cut Line= 2
     2081474.007      352039.774     2082669.053      353199.558
#Sta/Elev= 30
     9.9 1127.26   138.8 1119.67   198.3 1112.08   237.9 1102.94   317.2 1074.81
     337  1070.8   426.2  1072.4     456 1064.96   505.5 1070.33   644.3 1068.36
   703.8 1061.39   773.2 1063.34   822.7 1071.43   941.7 1075.22  1090.4 1068.64
  1140.2 1061.97  1155.2 1061.77  1189.5 1061.26  1199.4 1062.01  1229.2 1080.18
    1249 1085.05  1308.5 1126.04  1377.8 1153.36  1417.5 1176.96    1477 1205.23
  1496.8  1220.6  1546.4 1248.15    1586  1261.2  1645.5 1272.09  1665.3 1281.08
#Mann= 3 , 0 , 0
       0      .1       0  1140.2    .045       0  1155.2      .1       0
Bank Sta=1140.2,1155.2
XS Rating Curve= 0 ,0
Exp/Cntr=0.3,0.1

Type RM Length L Ch R = 1 ,12989.1 ,1212.2,1205.5,1198.9
XS GIS Cut Line= 2
     2080661.226      352647.415     2081448.507      353638.706
#Sta/Elev= 30
     9.9 1219.53    19.8 1214.74    39.6 1209.41   197.8 1152.62   207.7 1147.39
   237.4  1126.9   247.2 1123.19     267 1112.12   326.4 1084.05   346.1 1072.94
     356 1071.25   395.6 1056.09   415.4 1054.96   454.9 1058.17   563.7 1052.11
   623.1  1050.9   634.1 1050.91   649.1 1050.95   712.1 1051.38   781.3 1064.56
   840.6 1071.44   880.2  1084.7     900 1089.11   959.3 1110.08   998.9 1121.62
  1008.8 1122.42  1097.8 1144.67  1117.5 1146.78  1206.5 1165.83  1265.9  1174.9
#Mann= 3 , 0 , 0
       0      .1       0   634.1    .045       0   649.1      .1       0
Bank Sta=634.1,649.1
XS Rating Curve= 0 ,0
Exp/Cntr=0.3,0.1

Type RM Length L Ch R = 1 ,11783.6 ,880.6,871,861.4
XS GIS Cut Line= 2
     2079785.207      353632.696     2080740.428      354292.612
#Sta/Elev= 30
     9.9 1237.52    29.8 1219.04    49.6 1213.46    59.5 1214.48    99.2 1229.69
     129  1227.6   138.9 1223.81   168.7 1199.81   188.5 1177.97   208.4 1164.73
     258 1122.36   267.9 1108.27   277.8 1097.91   307.6 1073.31   357.2 1044.64
   367.2 1040.73     387 1039.02   430.3 1039.18   445.3 1039.74   625.2 1058.92
   654.9 1059.25   704.5 1054.74   724.4 1057.38   853.4 1095.24   922.9 1110.74
   992.3 1133.96  1022.1 1148.01  1091.5 1171.15  1111.4 1180.41    1161 1193.53
#Mann= 3 , 0 , 0
       0      .1       0   430.3    .045       0   445.3      .1       0
Bank Sta=430.3,445.3
XS Rating Curve= 0 ,0
Exp/Cntr=0.3,0.1

Type RM Length L Ch R = 1 ,10912.6 ,1075.2,1046.5,1017.8
XS GIS Cut Line= 2
     2079215.338       354574.57     2080422.769      354793.438
#Sta/Elev= 30
     9.9 1194.85    39.6 1193.35    49.5 1197.34    59.4 1210.08    69.3 1230.55
    79.2 1242.57    89.1 1251.72      99 1253.94   128.6 1239.36   138.5 1230.78
   197.9 1207.03   207.8 1198.55   336.5 1135.43   356.3 1121.49   405.7 1097.69
   425.5 1082.97     475 1057.57   494.8 1041.11   524.5 1036.15   653.4 1039.95
   668.4 1041.46   752.1 1052.02   831.3 1048.24   841.2 1050.53   900.5 1069.08
   969.8 1103.57   989.6 1116.94  1058.9 1145.48  1167.7 1171.24  1227.1 1180.36
#Mann= 3 , 0 , 0
       0      .1       0   653.4    .045       0   668.4      .1       0
Bank Sta=653.4,668.4
XS Rating Curve= 0 ,0
Exp/Cntr=0.3,0.1

Type RM Length L Ch R = 1 ,9866.1  ,859,847.7,836.4
XS GIS Cut Line= 3
      2079581.65      356773.247     2079835.309      356424.628
     2080488.695      355213.668
#Sta/Elev= 30
     9.8 1381.59    58.8 1374.01   176.4 1344.67   264.6 1317.67   352.7 1296.95
   401.7 1276.07   530.1 1245.95   549.9 1235.21   599.4 1190.59     639  1166.8
   678.6  1164.7   698.4 1154.41   718.2 1148.61   797.4 1105.83   817.2 1100.84
   906.3 1062.87   945.9 1049.27  1143.9 1050.77  1252.8  1040.3  1302.3 1028.71
  1362.8 1029.39  1377.8 1029.59  1391.4 1030.82  1411.2 1041.94  1440.9 1047.97
  1480.4 1082.48  1510.1 1094.57  1529.9 1098.38    1619 1135.84  1807.1 1168.39
#Mann= 3 , 0 , 0
       0      .1       0  1362.8    .045       0  1377.8      .1       0
Bank Sta=1362.8,1377.8
XS Rating Curve= 0 ,0
Exp/Cntr=0.3,0.1