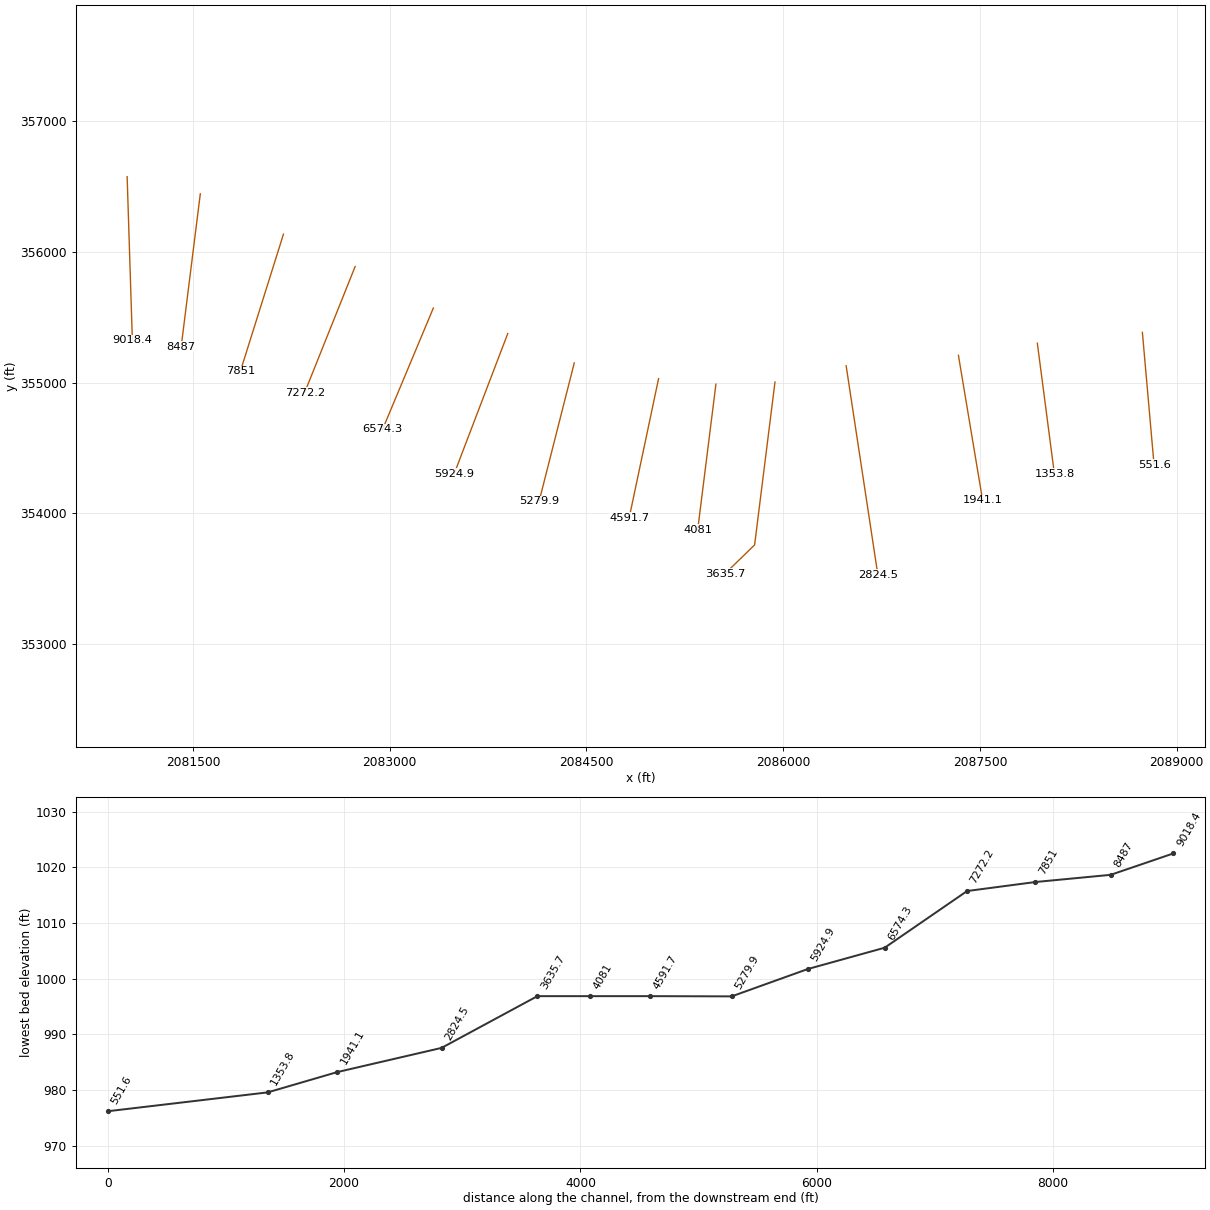
HEC-RAS study NBPOTRVR1.prj: NBPOTRVR1

--- NBPOTRVR1.g01 (geometry) --- (continued)

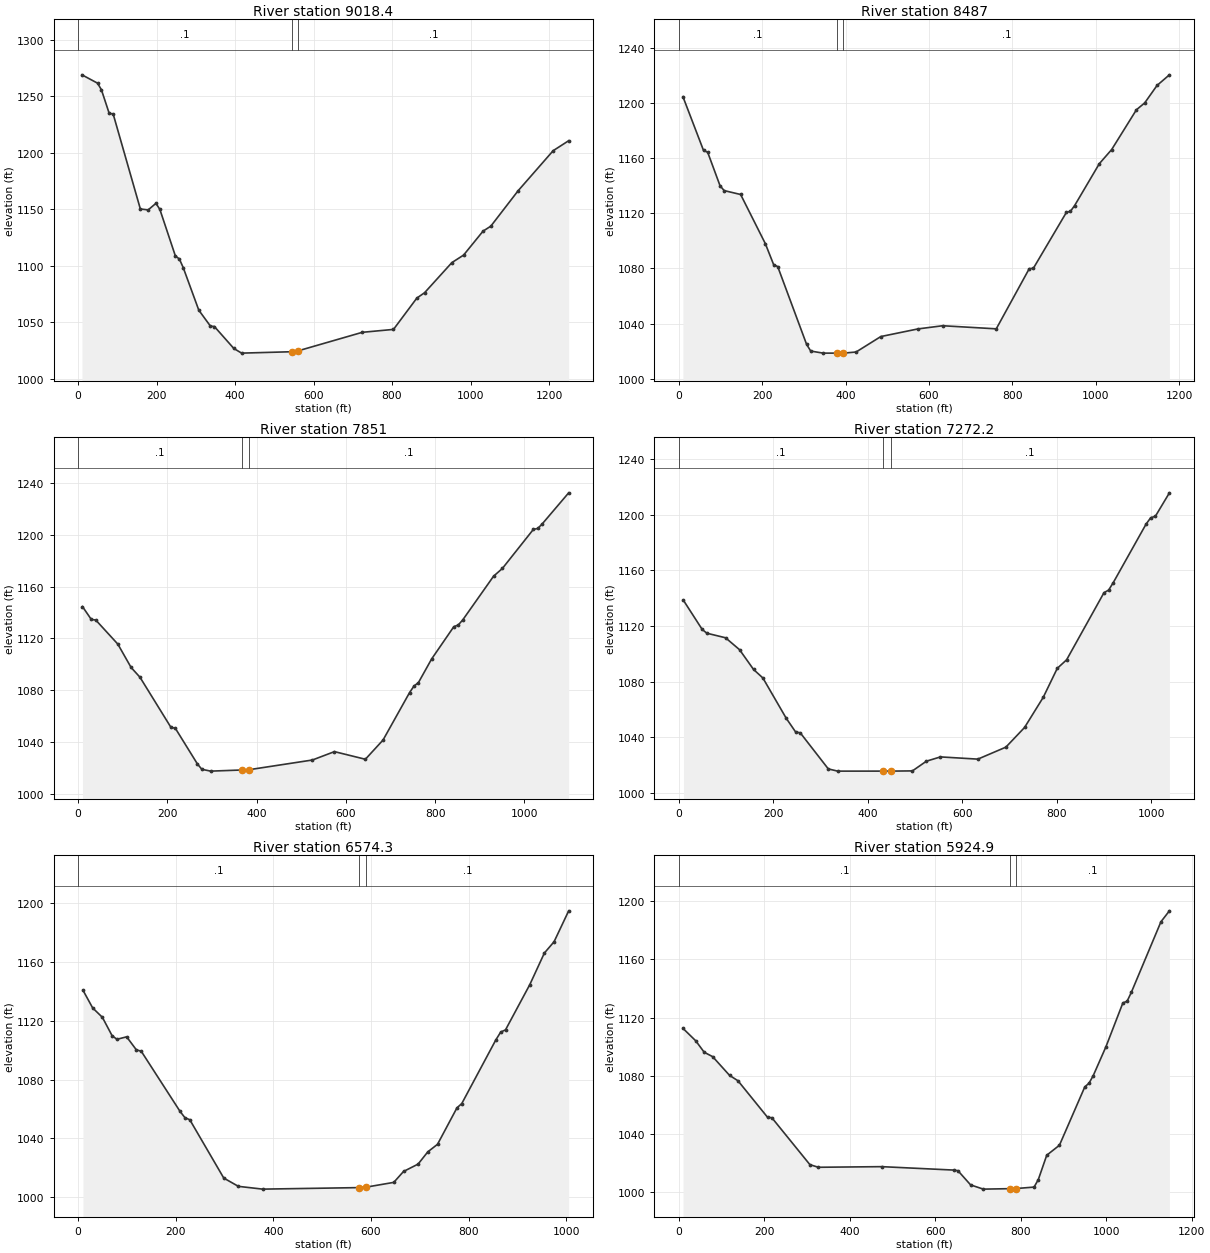
Type RM Length L Ch R = 1 ,9018.4  ,534.3,531.4,528.6
XS GIS Cut Line= 2
     2080997.716      356574.227     2081037.527      355324.714
#Sta/Elev= 30
     9.9 1268.84    49.6 1261.46    59.5 1255.61    79.4 1234.62    89.3 1234.31
   158.7 1150.09   178.6 1149.29   198.4 1155.08   208.4 1149.74     248 1108.49
     258  1105.9   267.9 1098.24   307.6 1060.55   337.3 1046.38   347.3 1046.07
   396.9 1026.62   416.7 1022.51   545.2 1023.75   560.2 1024.49   724.3 1040.94
   803.7 1043.51   863.2 1071.22     883    1076   952.5 1102.64   982.3 1109.28
  1031.9 1130.49  1051.7 1134.89  1121.2 1166.21  1210.5 1201.68  1250.1 1210.52
#Mann= 3 , 0 , 0
       0      .1       0   545.2    .045       0   560.2      .1       0
Bank Sta=545.2,560.2
XS Rating Curve= 0 ,0
Exp/Cntr=0.3,0.1

Type RM Length L Ch R = 1 ,8487    ,640.2,636,631.8
XS GIS Cut Line= 2
     2081555.653      356443.179     2081409.894      355275.563
#Sta/Elev= 30
     9.9 1204.49    59.3 1165.53    69.2 1164.26    98.9 1139.96   108.8 1136.44
   148.3 1133.61   207.6 1097.97   227.4 1082.83   237.3 1081.33   306.5 1025.02
   316.4 1020.16   346.1 1018.66   379.9 1018.66   394.9 1018.66   425.2 1019.47
   484.5 1030.67   573.5  1036.2   632.8 1038.51   761.4 1036.26   840.5 1079.85
   850.4 1080.14   929.5  1120.6   939.4 1121.47   949.3 1125.56  1008.6 1155.94
  1038.2 1166.18  1097.6 1195.02  1117.4 1199.96    1147 1212.63  1176.7 1220.33
#Mann= 3 , 0 , 0
       0      .1       0   379.9    .045       0   394.9      .1       0
Bank Sta=379.9,394.9
XS Rating Curve= 0 ,0
Exp/Cntr=0.3,0.1

Type RM Length L Ch R = 1 ,7851    ,580.5,578.8,577.1
XS GIS Cut Line= 2
     2082189.725      356135.116     2081860.995      355086.174
#Sta/Elev= 30
     9.9  1144.6    29.7 1134.64    39.6 1134.24    89.1 1115.59   118.8 1097.54
   138.6 1090.02     208 1051.26   217.9 1050.52   267.4 1022.91   277.3 1018.78
   297.1 1017.37   367.9 1018.26   382.9 1018.46   524.9 1025.96   574.4 1032.45
   643.7 1026.55   683.3 1041.43   742.7 1078.11   752.6 1083.17   762.5  1085.8
   792.2 1104.15   841.8 1129.06   851.7 1130.37   861.6  1134.2   930.9 1168.11
   950.7 1174.14    1020 1204.29  1029.9 1205.05  1039.8 1208.52  1099.2  1232.6
#Mann= 3 , 0 , 0
       0      .1       0   367.9    .045       0   382.9      .1       0
Bank Sta=367.9,382.9
XS Rating Curve= 0 ,0
Exp/Cntr=0.3,0.1

Type RM Length L Ch R = 1 ,7272.2  ,697.9,697.9,698
XS GIS Cut Line= 2
     2082736.168      355887.178     2082351.049      354923.317
#Sta/Elev= 30
     9.9 1138.43    49.4  1117.6    59.3 1114.85    98.9 1111.57   128.5 1103.01
   158.2 1088.78   177.9 1082.68   227.4 1053.67   247.1 1043.91     257 1043.26
   316.3 1017.34   336.1 1015.75     433 1015.76     448 1015.76   494.3 1015.92
   523.9 1022.89   553.6 1025.97   632.7 1024.37     692 1032.98   731.5  1047.1
   771.1 1068.81   800.7 1089.59   820.5 1095.74   899.6 1143.99   909.4 1145.82
   919.3 1151.27   988.5 1193.18   998.4 1197.82  1008.3 1198.87    1038 1215.72
#Mann= 3 , 0 , 0
       0      .1       0     433    .045       0     448      .1       0
Bank Sta=433,448
XS Rating Curve= 0 ,0
Exp/Cntr=0.3,0.1

Type RM Length L Ch R = 1 ,6574.3  ,649,649.3,649.7
XS GIS Cut Line= 2
     2083332.539      355569.911     2082945.383      354642.396
#Sta/Elev= 30
      10 1140.77    29.9 1128.72    49.8 1122.33    69.7 1109.86    79.6 1107.39
    99.5 1109.08   119.4 1100.23   129.4 1099.29     209 1058.35   218.9 1054.13
   228.9  1052.7   298.5 1013.07   328.4 1007.45   378.1 1005.56   575.3 1006.59
   590.3 1006.92   646.8 1010.15   666.7 1017.55   696.6 1022.58   716.5  1030.9
   736.4 1036.03   776.2  1060.8   786.1 1063.73   855.8 1106.96   865.8 1112.29
   875.7 1113.83   925.5  1144.6   955.3 1166.04   975.2 1173.73  1005.1 1194.72
#Mann= 3 , 0 , 0
       0      .1       0   575.3    .045       0   590.3      .1       0
Bank Sta=575.3,590.3
XS Rating Curve= 0 ,0
Exp/Cntr=0.3,0.1

Type RM Length L Ch R = 1 ,5924.9  ,642.4,645,647.6
XS GIS Cut Line= 2
     2083899.955      355374.999      2083491.27      354302.432
#Sta/Elev= 30
     9.9 1112.49    39.6 1103.97    59.4 1096.07    79.2 1093.04   118.7 1080.16
   138.5  1076.4   207.8 1051.19   217.7 1050.95   306.7 1018.61   326.5  1016.8
   474.9 1017.23   643.2 1014.87   653.1 1014.43   682.7 1004.65   712.4 1001.74
   774.4 1002.06   789.4 1002.16   831.2 1003.14   841.1 1008.34   860.8  1025.1
   890.5 1031.99   949.9 1072.24   959.8 1074.76   969.7 1080.04   999.4 1099.94
  1038.9 1130.06  1048.8 1131.24  1058.7 1137.35    1128 1186.01  1147.8 1193.54
#Mann= 3 , 0 , 0
       0      .1       0   774.4    .045       0   789.4      .1       0
Bank Sta=774.4,789.4
XS Rating Curve= 0 ,0
Exp/Cntr=0.3,0.1

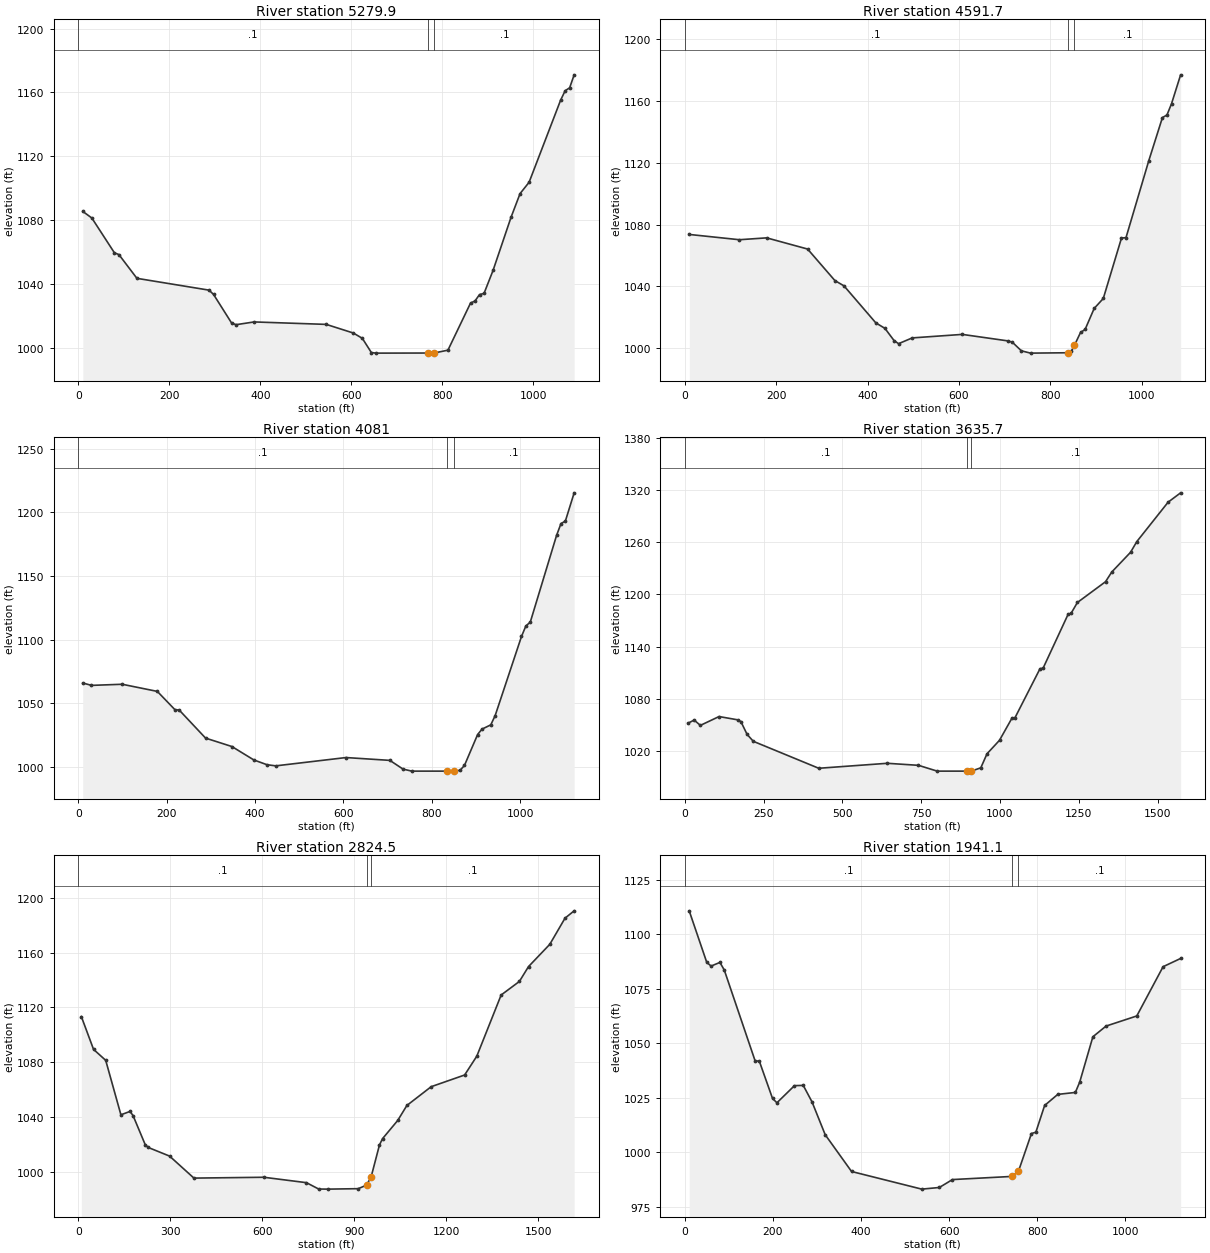
Type RM Length L Ch R = 1 ,5279.9  ,687.3,688.2,689.1
XS GIS Cut Line= 2
     2084407.012      355150.163     2084139.402      354093.694
#Sta/Elev= 30
     9.9 1085.51    29.7 1081.41    79.3 1059.63    89.2 1058.51   128.8 1043.64
   287.3 1036.25   297.2 1033.57   336.9 1015.66   346.8 1014.63   386.4 1016.35
   544.9 1014.81   604.4 1009.41   624.2 1006.09     644  997.21   653.9  996.82
   767.5  996.88   782.5  996.92   812.4  998.68     862 1028.13   871.9  1029.5
   881.8 1033.48   891.7 1034.21   911.5 1048.57   951.1 1081.89   970.9 1096.69
   990.8 1103.81  1060.1 1155.24    1070 1161.08  1079.9 1162.94  1089.8 1171.05
#Mann= 3 , 0 , 0
       0      .1       0   767.5    .045       0   782.5      .1       0
Bank Sta=767.5,782.5
XS Rating Curve= 0 ,0
Exp/Cntr=0.3,0.1

Type RM Length L Ch R = 1 ,4591.7  ,508.9,510.8,512.7
XS GIS Cut Line= 2
     2085049.925      355030.018     2084826.399      353968.532
#Sta/Elev= 30
      10 1073.66   119.4 1070.25   179.1 1071.46   268.7 1064.22   328.4 1043.81
   348.3 1040.39     418 1016.42   437.9 1012.88   457.8    1005   467.7 1002.98
   497.6 1006.71   607.1 1008.98   706.6 1004.79   716.5 1003.95   736.4  998.35
   756.4  996.86   837.6   997.1   845.9  998.23   852.6 1001.97   865.8 1010.22
   875.8 1012.19   895.7  1025.8   915.6 1032.22   955.4 1071.32   965.3 1071.61
  1015.1 1121.37    1045 1149.31  1054.9 1150.96  1064.9 1158.28  1084.8 1176.97
#Mann= 3 , 0 , 0
       0      .1       0   837.6    .045       0   852.6      .1       0
Bank Sta=837.6,852.6
XS Rating Curve= 0 ,0
Exp/Cntr=0.3,0.1

Type RM Length L Ch R = 1 ,4081    ,445.2,445.2,445.2
XS GIS Cut Line= 2
     2085487.311      354988.387     2085348.306       353874.87
#Sta/Elev= 30
     9.9 1066.08    29.8 1064.19    99.3 1065.07   178.8 1059.46   218.5 1045.15
   228.4 1044.79     288 1022.79   347.6 1016.17   397.2 1005.64     427 1001.89
   446.9    1001   605.8 1007.52   705.1  1005.3   734.9  998.45   754.7  996.86
   835.4  996.86   850.4  996.86     864   997.5   873.9 1001.31   903.7 1025.58
   913.6 1029.84   933.5  1033.2   943.4 1040.46    1003  1102.6  1012.9 1110.84
  1022.9 1113.87  1082.4 1181.96  1092.4 1191.25  1102.3  1193.2  1122.2 1215.39
#Mann= 3 , 0 , 0
       0      .1       0   835.4    .045       0   850.4      .1       0
Bank Sta=835.4,850.4
XS Rating Curve= 0 ,0
Exp/Cntr=0.3,0.1

Type RM Length L Ch R = 1 ,3635.7  ,805,811.2,817.5
XS GIS Cut Line= 3
     2085937.708      355004.742     2085782.203      353759.048
     2085554.756       353537.29
#Sta/Elev= 30
     9.9 1051.85    29.7 1055.53    49.4 1049.42   108.7 1059.57     168 1055.79
   177.9  1053.8   197.7 1039.03   217.5 1031.09     425 1000.14   642.5 1005.86
   741.4 1003.52   800.7  996.86   893.9  996.86   908.9  996.86   939.1 1000.67
   958.8 1016.81   998.4  1032.3  1037.9 1057.72  1047.8 1058.41  1126.9 1114.53
  1136.7 1115.13  1215.8 1176.86  1225.7 1178.32  1245.5 1190.61  1334.8  1214.5
  1354.6 1225.65  1414.2 1248.31    1434 1260.59  1533.3 1305.88    1573 1316.62
#Mann= 3 , 0 , 0
       0      .1       0   893.9    .045       0   908.9      .1       0
Bank Sta=893.9,908.9
XS Rating Curve= 0 ,0
Exp/Cntr=0.3,0.1

Type RM Length L Ch R = 1 ,2824.5  ,883.1,883.4,883.7
XS GIS Cut Line= 2
     2086480.317      355128.418      2086722.25      353529.045
#Sta/Elev= 30
     9.9 1113.35    49.6 1089.47    89.3 1081.48   138.9 1041.76   168.7 1044.22
   178.6 1041.15   218.3 1019.94   228.2 1017.93   297.7 1011.64   377.1   995.6
   605.3  996.21   744.3  992.26     784  987.64   813.7  987.56     913  987.89
   940.2  990.46   955.2  996.45   982.4 1019.73   992.4 1024.35    1042 1037.64
  1071.8 1048.55  1151.2 1062.26  1260.3 1070.78    1300 1084.51  1379.4 1129.11
  1438.9    1139  1468.7 1149.82  1538.2 1166.09  1587.8 1185.14  1617.6 1190.49
#Mann= 3 , 0 , 0
       0      .1       0   940.2    .045       0   955.2      .1       0
Bank Sta=940.2,955.2
XS Rating Curve= 0 ,0
Exp/Cntr=0.3,0.1

Type RM Length L Ch R = 1 ,1941.1  ,588.1,587.3,586.4
XS GIS Cut Line= 2
     2087336.352      355209.102     2087521.083      354099.243
#Sta/Elev= 30
      10 1110.76    49.8 1087.15    59.7 1085.44    79.7 1087.12    89.6 1083.62
   159.3 1042.15   169.3 1041.75   199.1 1024.75   209.1 1022.79   248.9 1030.64
   268.8 1030.75   288.7 1023.19   318.6 1008.14   378.4  991.29   537.7  983.21
   577.5  983.96   607.4  987.59     742  989.03     757  991.33   786.6 1008.69
   796.6  1009.3   816.5 1021.55   846.3 1026.63   886.2 1027.52   896.1 1032.25
     926 1053.04   955.9 1057.94  1025.6 1062.57  1085.3 1085.15  1125.1 1088.93
#Mann= 3 , 0 , 0
       0      .1       0     742    .045       0     757      .1       0
Bank Sta=742,757
XS Rating Curve= 0 ,0
Exp/Cntr=0.3,0.1

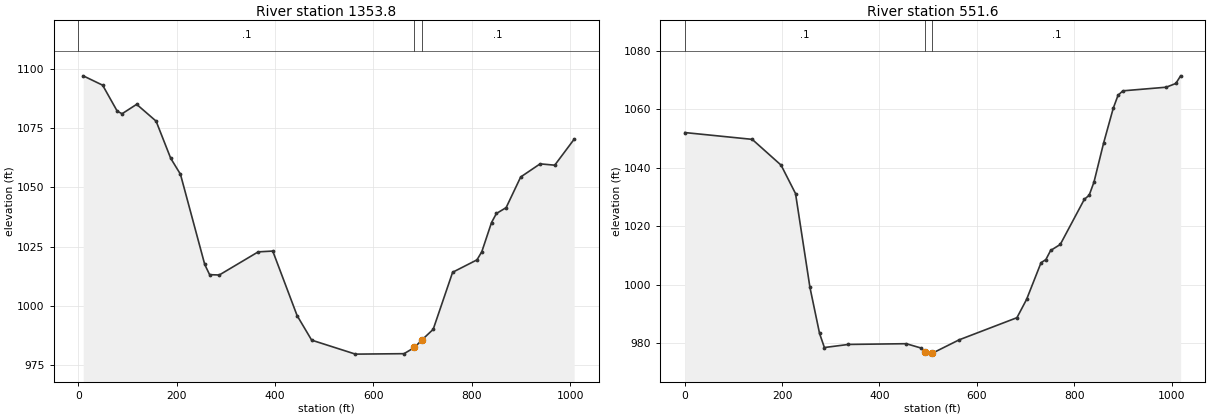
Type RM Length L Ch R = 1 ,1353.8  ,1352.8,1353.8,1354.8
XS GIS Cut Line= 2
     2087938.182      355301.028     2088068.225      354301.319
#Sta/Elev= 30
     9.9 1097.14    49.4 1093.19    79.1  1082.2      89 1081.13   118.6  1085.1
   158.1    1078   187.8 1062.31   207.6 1055.57     257 1017.46   266.9 1013.14
   286.6    1013   365.7 1022.77   395.3 1023.11   444.8  995.85   474.4  985.48
   563.4  979.57   662.2  979.76   683.4  982.38   698.4  985.54   721.5  990.05
     761 1014.15   810.5 1019.39   820.3 1022.82   840.1 1035.16     850 1038.98
   869.8 1041.46   899.4 1054.41   938.9 1059.95   968.6 1059.39  1008.1 1070.37
#Mann= 3 , 0 , 0
       0      .1       0   683.4    .045       0   698.4      .1       0
Bank Sta=683.4,698.4
XS Rating Curve= 0 ,0
Exp/Cntr=0.3,0.1

Type RM Length L Ch R = 1 ,551.6   ,549.5,551.6,553.7
XS GIS Cut Line= 2
     2088739.083      355384.444     2088828.233      354369.673
#Sta/Elev= 30
       0 1052.07   138.5 1049.74   197.8 1040.91   227.5 1031.18   257.1  999.05
   276.9  983.25   286.8  978.44   336.3   979.5   454.9  979.75   484.6  978.31
   493.8  976.95   504.4  976.18   508.8  976.51   563.7  981.08   682.4  988.66
   702.2  994.92   731.9 1007.49   741.8 1008.56   751.6 1011.68   771.4 1013.74
   820.9 1029.21   830.8  1030.6   840.7 1035.12   860.4 1048.44   880.2 1060.36
   890.1 1064.83     900 1066.36     989  1067.6  1008.8 1068.88  1018.7  1071.5
#Mann= 3 , 0 , 0
       0      .1       0   493.8    .045       0   508.8      .1       0
Bank Sta=493.8,508.8
XS Rating Curve= 1 ,0
   31003     980
Exp/Cntr=0.3,0.1

Chan Stop Cuts=-1
Use User Specified Reach Order=0